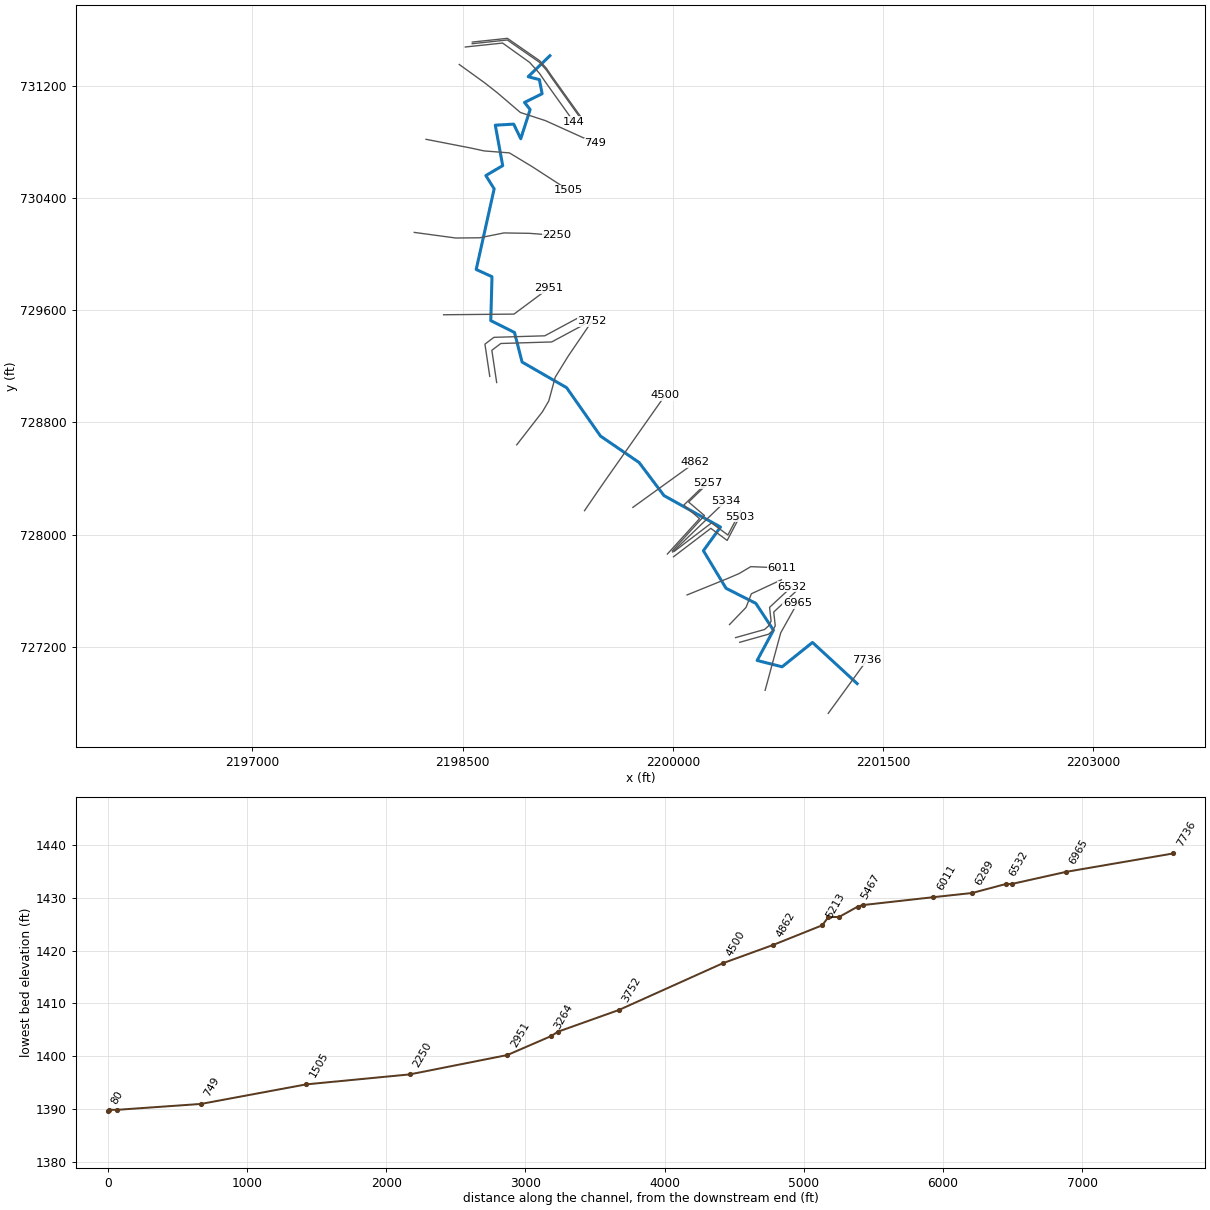
--- CHILDERSRN.prj (project) ---

Proj Title=CHILDERSRN
Current Plan=p01
Default Exp/Contr=0.3,0.1
English Units
Geom File=g01
Flow File=f01
Plan File=p01
Y Axis Title=Elevation
X Axis Title(PF)=Main Channel Distance
X Axis Title(XS)=Station
BEGIN DESCRIPTION:
---------- MODELED AS PART OF WVEMD CTP PROGRAM, 2023----------
Stream Name: Childers Run
Flood Zone:  AFH
Upshur County, WV
HEC-RAS Version: RAS 6.3
Vertical Datum: NAVD88
Projection: NAD 1983 StatePlane West Virginia S FIPS 4702 (US Feet)
Terrain: 1-meter LIDAR (FEMA Region III 3DEP collected 2016-2018)
Land Use: 2019 NLCD
Hydrologic Method:
WV SIR2010-5033 regression equations
Additional Model Notes:
None
END DESCRIPTION:
DSS Export Rating Curves= 0
DSS Export Rating Curve Sorted= 0
DSS Export Volume Flow Curves= 0
DXF OffsetX= 0
DXF OffsetY= 0
DXF ScaleX= 1
DXF ScaleY= 10

--- CHILDERSRN.p01 (plan) ---

Plan Title=Floodplain
Program Version=6.31
Short Identifier=Floodplain
Geom File=g01
Flow File=f01
Subcritical Flow
K Sum by GR= 0
Std Step Tol= 0.01
Critical Tol= 0.01
Num of Std Step Trials= 20
Max Error Tol= 0.3
Flow Tol Ratio= 0.001
Split Flow NTrial= 30
Split Flow Tol= 0.02
Split Flow Ratio= 0.02
Log Output Level= 0
Friction Slope Method= 1
Unsteady Friction Slope Method= 2
Unsteady Bridges Friction Slope Method= 1
Parabolic Critical Depth
Global Vel Dist= 0 , 0 , 0
Global Log Level= 0
CheckData=True
Encroach Param=-1 ,0,0, 0
Computation Interval=1MIN
Output Interval=1HOUR
Instantaneous Interval=1HOUR
Mapping Interval=1HOUR
Computation Time Step Use Courant=        0
Computation Time Step Use Time Series=    0
Computation Time Step Count To Double=0
Computation Time Step Max Doubling=0
Computation Time Step Max Halving=0
Computation Time Step Residence Courant=0
Run HTab= 0
Run UNet= 0
Run Sediment= 0
Run PostProcess= 0
Run WQNet= 0
Run RASMapper= 0
UNET Theta= 1
UNET Theta Warmup= 1
UNET ZTol= 0.02
UNET ZSATol= 0.02
UNET MxIter= 20
UNET Max Iter WO Improvement= 0
UNET MaxInSteps= 0
UNET DtIC= 0
UNET DtMin= 0
UNET MaxCRTS= 20
UNET WFStab= 2
UNET SFStab= 1
UNET WFX= 1
UNET SFX= 1
UNET Gravity=32.17405
UNET 1D Methodology=Finite Difference
UNET DSS MLevel= 4
UNET Pardiso=0
UNET DZMax Abort= 100
UNET Use Existing IB Tables=-1
UNET Froude Reduction=False
UNET Froude Limit= 0.8
UNET Froude Power= 4
UNET D1 Cores= 0
UNET WindReference=Eulerian
UNET WindDragFormulation=Hsu (1988)
UNET D2 Coriolis=0
UNET D2 Cores= 0
UNET D2 Theta= 1
UNET D2 Theta Warmup= 1
UNET D2 Z Tol= 0.01
UNET D2 Volume Tol= 0.01
UNET D2 Max Iterations= 20
UNET D2 Equation= 0
UNET D2 RampUpFraction=0.1
UNET D2 TimeSlices= 1
UNET D2 Turbulence Formulation=None
UNET D2 Eddy Viscosity=0.3
UNET D2 Transverse Eddy Viscosity=0.1
UNET D2 Smagorinsky Mixing=0.05
UNET D2 BCVolumeCheck=0
UNET D2 Cores=0
UNET D2 SolverType=PARDISO (Direct)
UNET D2 Minimum Iterations= 3
UNET D2 Maximum Iterations= 30
UNET D2 Restart Number= 10
UNET D2 Relaxation Coeff=1.3
UNET D2 SOR Precondition Iterations= 10
UNET D2 ILUT Maximum Fill= 8
UNET D2 ILUT Tolerance=1E-08
UNET D2 Convergence Tolerance=0.00001
UNET D1D2 MaxIter= 0
UNET D1D2 ZTol=0.01
UNET D1D2 QTol=0.1
UNET D1D2 MinQTol=1
Write IC File= 0
Write IC File at Fixed DateTime=0
Write IC File at Sim End=0
Echo Input=False
Echo Parameters=False
Echo Output=False
Write Detailed= 0
HDF Write Warmup=0
HDF Write Time Slices=0
HDF Flush=0
HDF Compression= 1
HDF Chunk Size= 1
HDF Spatial Parts= 1
HDF Use Max Rows=0
HDF Fixed Rows= 1
Calibration Method= 0
Calibration Iterations= 20
Calibration Max Change=0.05
Calibration Tolerance=0.2
Calibration Maximum=1.5
Calibration Minimum=0.5
Calibration Optimization Method= 1
WQ AD Non Conservative
WQ ULTIMATE=-1
WQ Max Comp Step=1HOUR
WQ Output Interval=15MIN
WQ Output Selected Increments= 0
WQ Create Restart=0
WQ Fixed Restart=0
WQ System Summary=0
WQ Write To DSS=0
Sorting and Armoring Iterations= 10
XS Update Threshold= 0.02
Bed Roughness Predictor= 0
Hydraulics Update Threshold= 0.02
Energy Slope Method= 1
Volume Change Method= 1
Sediment Retention Method= 0
Sediment TS Multiplier= 1
Warm Up Method= 0
XS Weighting Method= 0
Number of US Weighted Cross Sections= 1
Number of DS Weighted Cross Sections= 1
Upstream XS Weight=0
Main XS Weight=1
Downstream XS Weight=0
Number of DS XS's Weighted with US Boundary= 1
Upstream Boundary Weight= 1
Weight of XSs Associated with US Boundary= 0
Number of US XS's Weighted with DS Boundary= 1
Downstream Boundary Weight= 0.5
Weight of XSs Associated with DS Boundary= 0.5
Percentile Method= 0
Sediment Output Level= 3
Mass or Volume Output= 0
Output Increment Type= 1
Profile and TS Output Increment= 1
Transport Output Increment 1
XS Output Flag= 0
XS Output Increment= 10
Read HDF5 Sediment Hotstart= 0
Sediment Hotstart Type= 0
Write Gradation File= 0
Read Gradation Hotstart= 0
Write HDF5 File= 1
Write Binary Output= 1
Write DSS Sediment File= 0
DSS Sediment Output Type= 1
SV Curve= 0
Specific Gage Flag= 0
Subcell Erosion Methods= 0
Subcell Deposition Methods= 0
Advection Scheme= 1
Matrix Solver= 0
Implicit Weighting Factor= 1
Maximum Outer Loop Convergence Iterations= 5
Convergence Maximum Absolute= 0.001
Convergence RMSE= 0.0001
Grain Fractions Max Abs Error= 0.001
Max Subgrid Regions= 1
Max Subgrid Length Scale= 3.402823E+38
Initial Layer Thickness= 3.402823E+38
Min Layer Thickness= 3.402823E+38
Max Layer Thickness= 3.402823E+38
Number of Layers= 5

--- CHILDERSRN.f01 (steady flow) ---

Flow Title=Flow
Program Version=6.31
Number of Profiles= 1
Profile Names=01pct
River Rch & RM=CHILDERSRN,Main,7736
     382
River Rch & RM=CHILDERSRN,Main,2951
     559
Boundary for River Rch & Prof#=CHILDERSRN,Main            , 1
Up Type= 0
Dn Type= 3
Dn Slope=0.00428
DSS Import GetInterval= 0
DSS Import GetPeak= 0
DSS Import FillOption= 0

--- CHILDERSRN.g01 (geometry) ---

Geom Title=Geometry
Program Version=6.31

River Reach=CHILDERSRN      ,Main
Reach XY= 30
2201314.99621772726936.4700006322200995.92961185727230.377293333
2200779.18923168727056.6184545012200601.16662183727101.889689416
2200717.57813442727317.8863046772200591.60857008727509.243861586
2200379.21791875727616.8128721712200217.64967234727884.833989665
2200339.84168518728053.6420510112199936.49373859728278.109121755
2199759.04363418728514.0797784182199483.49628501728702.804794669
2199242.03121676729047.8611911682198924.04596034729230.834578499
2198869.93222342729441.7085005942198700.66648585729526.642057762
   2198709.42303729839.8769955932198596.61715326729891.443821594
2198724.76125392730466.7763323342198665.55402325730561.496615335
2198785.68567276730632.2363032552198732.91707751730920.718009755
2198864.09463668730928.3872857542198914.60240968730824.252323419
2198981.59341742731032.6938356762198941.55904867731083.058892429
2199066.98465084731145.4140826762199047.29669809731246.372542173
2198967.22796059731266.7475014182199122.41465808731416.296743006

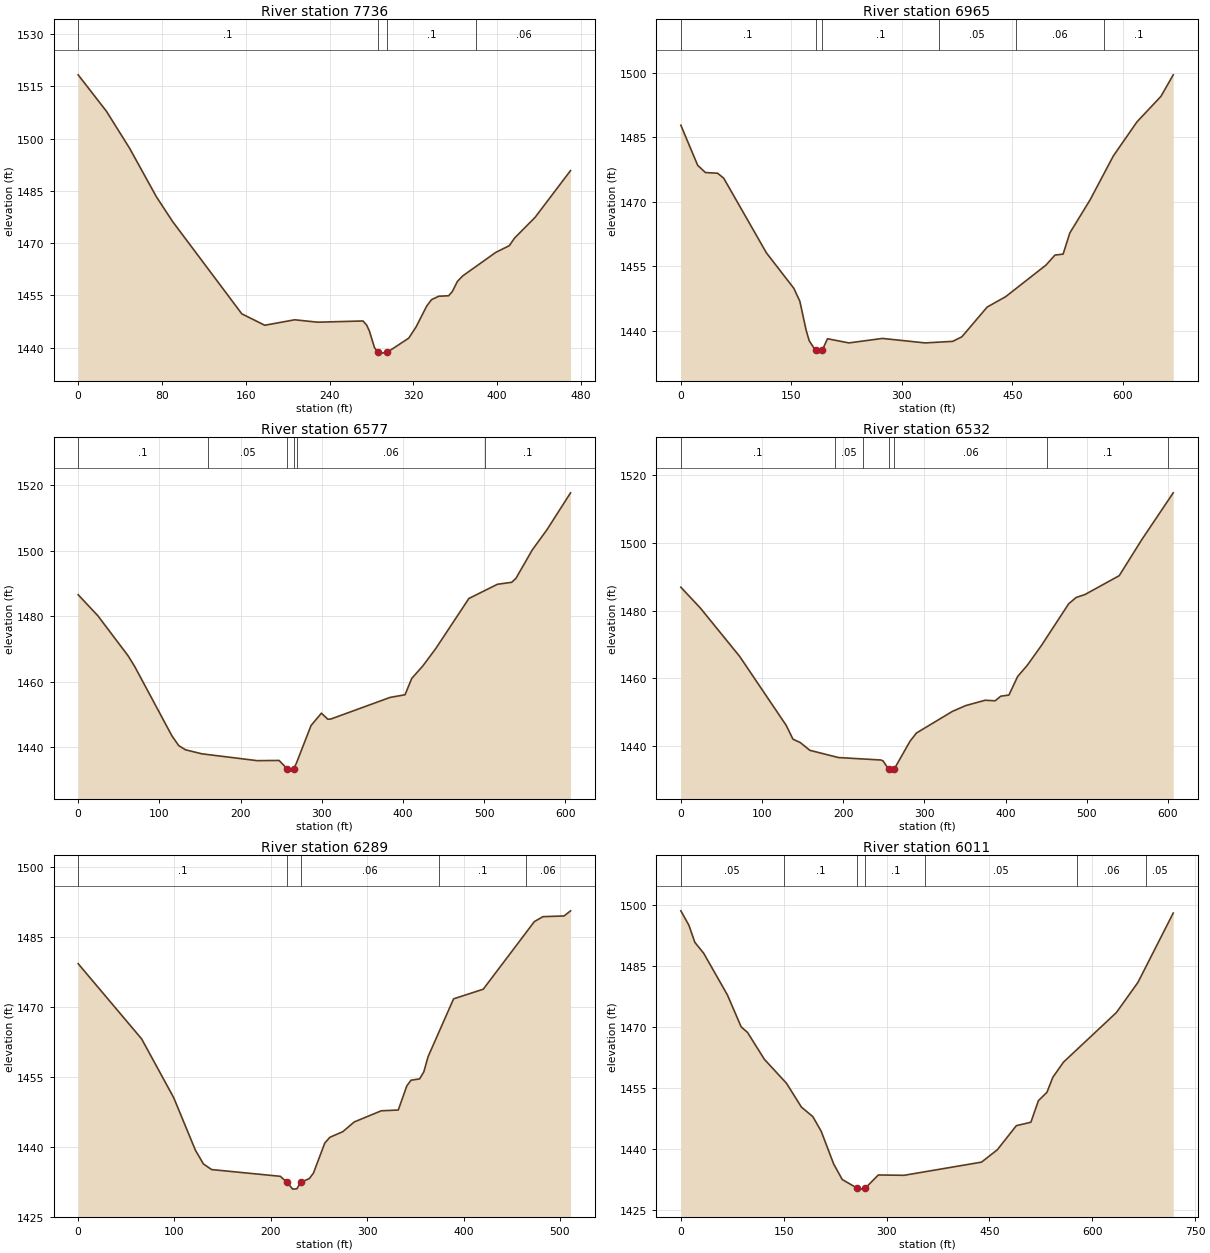
Type RM Length L Ch R = 1 ,7736    ,771.1,771.1,771.1
XS GIS Cut Line= 2
2201108.33119777726724.2987025692201384.60931421727104.497945383
#Sta/Elev= 30
       0 1518.28      27 1507.82    49.2 1497.15    74.6 1483.31    90.1 1476.19
   156.2 1449.67   178.1 1446.39   206.7 1447.96   228.5 1447.27   271.9 1447.62
   275.4 1446.42     278 1444.73   282.9 1439.93  286.24 1438.67   289.7 1438.39
   295.2 1438.67   315.5 1442.68   322.5 1445.89   332.7 1451.91   337.3 1453.74
   344.2 1454.72   353.6 1454.86   357.1 1456.06     362 1458.98     367 1460.54
   398.6 1467.31   411.5 1469.23   416.4 1471.37   436.2 1477.39469.9799  1490.8
#Mann= 4, -1 ,  0
       0     0.1       0  286.24   0.045       0   295.2     0.1       0
     380    0.06       0
Bank Sta=286.24,295.2
XS Rating Curve= 0 ,0
Exp/Cntr(USF)=0,0
Exp/Cntr=0.3,0.1

Type RM Length L Ch R = 1 ,6965    ,388,388.6,381.8
XS GIS Cut Line= 3
2200658.19008825 726888.981097162200769.27710981727298.907852785
2200888.18716106727511.694260286
#Sta/Elev= 30
       0 1487.78    22.9 1478.47    33.4  1476.8    49.9 1476.64    58.2 1475.49
   116.2 1458.16   153.5 1449.92   161.6 1446.92   170.1 1440.22   174.3 1437.76
  182.931435.519   186.7  1434.9  191.841435.528   199.1 1438.24   228.1 1437.27
   273.7 1438.31   331.7 1437.27     369 1437.63   381.5 1438.68   415.9 1445.59
   441.1 1448.01   495.8 1455.33   507.9 1457.65     519 1457.87   528.1 1462.78
   555.6 1470.45   587.2 1480.65   619.2 1488.54   651.9 1494.49   668.5 1499.47
#Mann= 6, -1 ,  0
       0     0.1       0  182.93   0.045       0  191.84     0.1       0
     350    0.05       0  454.71    0.06       0  574.71     0.1       0
Bank Sta=182.93,191.84
XS Rating Curve= 0 ,0
Exp/Cntr(USF)=0,0
Exp/Cntr=0.3,0.1

Type RM Length L Ch R = 1 ,6577    ,46.3,44.5,44.3
XS GIS Cut Line= 6
2200476.91188091727231.5053522382200683.43986466727289.395771926
2200710.03816559727312.8648609882200730.37804278727348.850797551
2200719.42580122727447.4209716142200877.45100091727594.493929739
#Sta/Elev= 30
       0 1486.53    24.2 1480.12    61.5 1467.87    69.9 1464.48   115.6 1443.36
   123.9 1440.42   132.2 1439.14   152.4 1437.91   220.5 1435.82   247.5 1435.88
   257.6  1433.3   262.4 1432.62  265.25 1433.31   268.7 1434.97   286.8 1446.53
   299.6 1450.33   307.6 1448.46   311.6 1448.57   384.3 1455.15   402.6 1455.95
   410.9 1460.95   424.5 1464.74   440.6 1470.12   481.3 1485.38   516.5 1489.72
     534 1490.32   539.2 1491.51   559.4 1500.23   577.5  1506.4   606.5 1517.66
#Mann= 6, -1 ,  0
       0     0.1       0     160    0.05       0   257.6   0.045       0
  265.25    0.05       0  269.96    0.06       0  500.67     0.1       0
Bank Sta=257.6,265.25
XS Rating Curve= 0 ,0
Exp/Cntr(USF)=0,0
Exp/Cntr=0.3,0.1

Type RM Length L Ch R = 1 ,6532    ,238,242.7,244.7
XS GIS Cut Line= 6
2200447.18436809727264.7614306762200653.71235184727322.651850363
2200680.31065278727346.1209394262200700.65052997727382.106875989
2200689.69828841727480.6770500512200847.72348809727627.750008176
#Sta/Elev= 30
       0 1486.95    23.9 1480.84    72.5 1466.49   129.8 1446.12   138.1 1442.05
   147.2 1441.03   158.9 1438.75   194.2 1436.61   246.4 1435.89   249.2  1435.6
  255.961433.156   258.1  1432.6   262.7 1433.15   282.2  1441.4   290.2 1443.86
   334.4 1450.24   350.7 1451.95   374.8 1453.55   387.1 1453.38   394.1 1454.75
   404.1 1455.07   414.9 1460.59   426.6 1463.83   444.3 1469.78   477.7 1482.04
   486.9 1483.91   497.9  1484.8     540 1490.36   567.5  1500.9   606.5 1514.84
#Mann= 7, -1 ,  0
       0     0.1       0     190    0.05       0  224.49    0.06       0
  255.96   0.045       0   262.7    0.06       0  450.67     0.1       0
  600.67    0.06       0
Bank Sta=255.96,262.7
XS Rating Curve= 0 ,0
Exp/Cntr(USF)=0,0
Exp/Cntr=0.3,0.1

Type RM Length L Ch R = 1 ,6289    ,284.4,278,266.7
XS GIS Cut Line= 4
2200403.80485562727357.7297241412200522.06202811727480.606317426
2200559.94127867 727577.61415423 2200774.2824038727677.393643514
#Sta/Elev= 30
       0 1479.29    65.9 1463.14    99.2 1450.52   121.7 1439.26     130 1436.31
   138.5  1435.1   209.8 1433.65  216.791432.382   222.7  1430.9     227 1430.97
  231.05 1432.38   239.9 1433.15   244.2 1434.33     256 1440.79   261.3 1442.03
   274.7 1443.23   286.6 1445.32   314.6 1447.71   332.3 1447.88   341.1 1453.04
   345.5 1454.28   354.4 1454.55   358.8 1456.07   363.2 1459.32   389.7 1471.74
   420.5 1473.81   473.5 1488.31   482.4 1489.38   504.4 1489.53   511.1 1490.63
#Mann= 5, -1 ,  0
       0     0.1       0  216.79   0.045       0  231.05    0.06       0
  374.68     0.1       0  464.68    0.06       0
Bank Sta=216.79,231.05
XS Rating Curve= 0 ,0
Exp/Cntr(USF)=0,0
Exp/Cntr=0.3,0.1

Type RM Length L Ch R = 1 ,6011    ,514.8,508.8,497.5
XS GIS Cut Line= 5
2200101.29983338727569.3671148552200394.69196917727688.406561002
2200472.97002783727722.1177796722200555.61159484727771.152458504
2200775.62472366727762.376006603
#Sta/Elev= 30
       0 1498.56    11.7 1495.04    20.4 1490.82    33.3 1488.13    67.9 1477.88
      88 1470.02    97.3 1468.64   121.8 1462.05   154.2 1456.12   175.8  1450.3
   192.5 1447.94   204.7 1444.34   222.9 1436.29   235.4 1432.47  256.721430.397
   263.1 1430.11   269.2 1430.39     288 1433.59   325.6 1433.51   438.5 1436.75
   461.4 1439.76   489.3 1445.72   510.5 1446.56   521.5 1451.87     534 1453.94
   542.5 1457.62   558.1 1461.35   635.1 1473.52   666.6 1480.94   718.1 1498.01
#Mann= 7, -1 ,  0
       0    0.05       0     150     0.1       0  256.72   0.045       0
   269.2     0.1       0  356.62    0.05       0  577.94    0.06       0
  677.94    0.05       0
Bank Sta=256.72,269.2
XS Rating Curve= 0 ,0
Exp/Cntr(USF)=0,0
Exp/Cntr=0.3,0.1

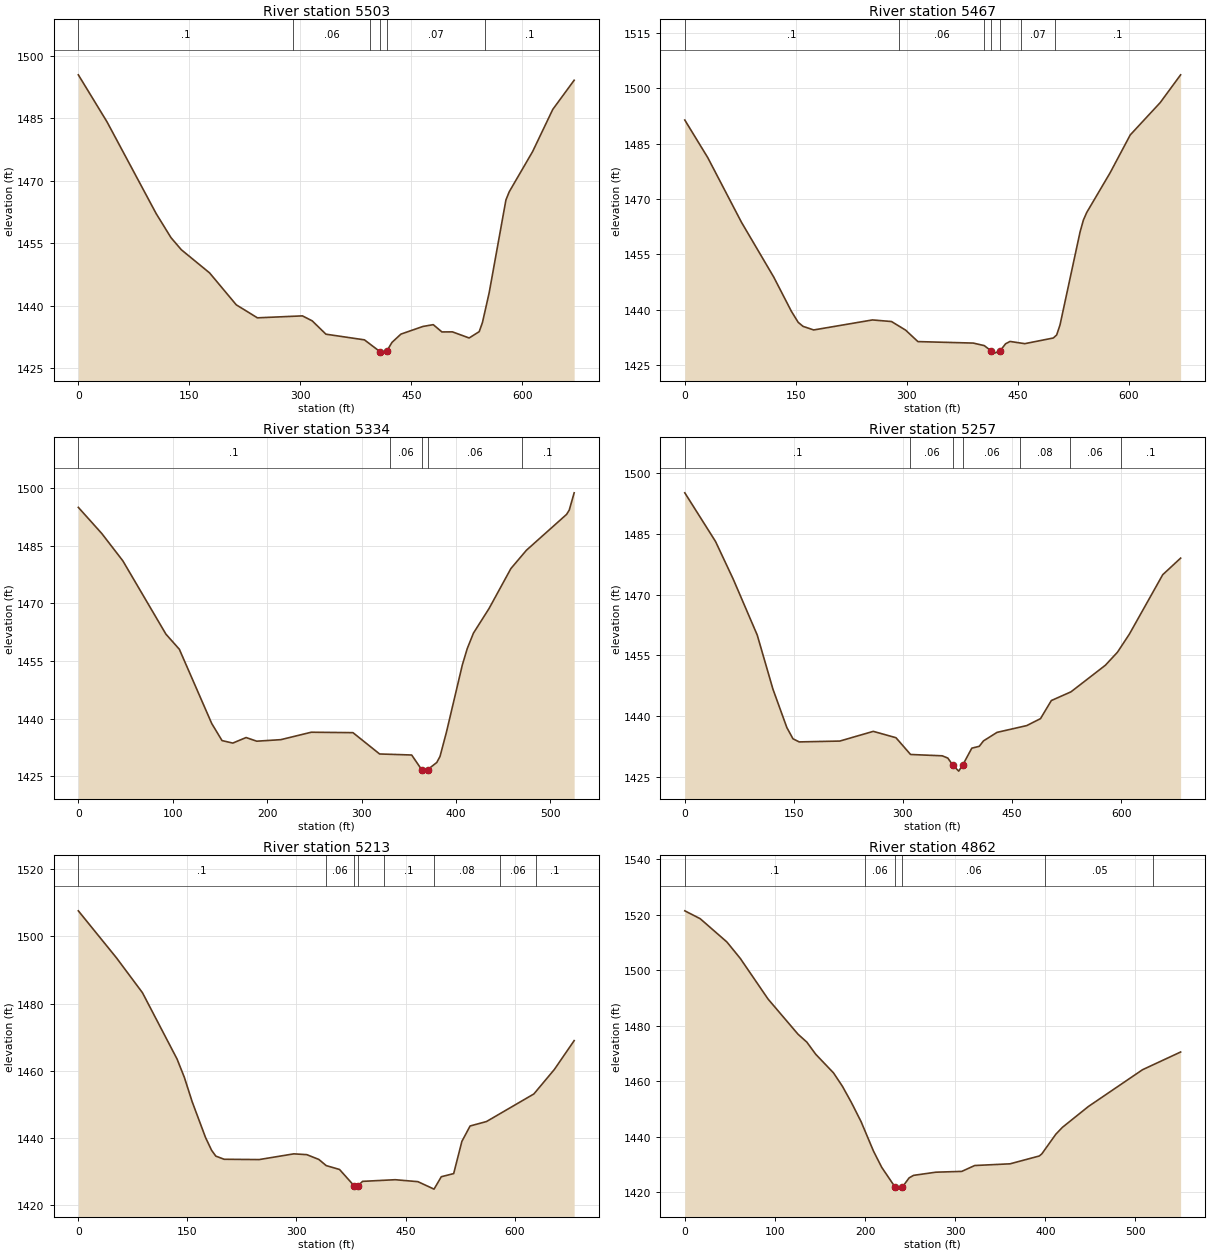
Type RM Length L Ch R = 1 ,5503    ,37.2,35.9,35.3
XS GIS Cut Line= 4
2200004.55721125727841.6718574972200270.69668122728044.444786997
2200387.29111568 727958.266291962200476.00427234728126.821289607
#Sta/Elev= 30
       0 1495.48    38.8 1484.17   105.1 1462.16   125.2 1456.36   139.2 1453.45
   177.4 1447.88   213.4 1440.22     242 1437.09   302.8 1437.56     316 1436.37
   334.6 1433.16   386.6  1431.8   407.4    1429     411 1428.61  416.51 1429.01
   423.8 1431.18   435.9 1433.18   465.7 1435.02   479.6 1435.45   491.3  1433.7
   505.5 1433.72   528.1 1432.25   541.7 1433.77   546.1 1435.98   555.2 1443.15
   577.8 1465.41   582.3 1467.39   613.9 1477.05   641.1 1487.17     670 1494.18
#Mann= 6, -1 ,  0
       0     0.1       0     290    0.06       0  394.58    0.07       0
   407.4   0.045       0  416.51    0.07       0  549.57     0.1       0
Bank Sta=407.4,416.51
XS Rating Curve= 0 ,0
Exp/Cntr(USF)=0,0
Exp/Cntr=0.3,0.1

Type RM Length L Ch R = 1 ,5467    ,114.8,132.4,145.7
XS GIS Cut Line= 4
2200009.62653449727880.3254471832200275.76600446728083.098376683
2200392.36043892727996.9198816462200481.07359558728165.474879293
#Sta/Elev= 30
       0 1491.38      31 1481.22    76.6 1463.71   120.2 1448.88     144 1439.64
   153.2 1436.65   159.8 1435.55   174.2 1434.58   253.6 1437.29   279.3 1436.86
   298.4 1434.53     315 1431.43   389.8 1431.03   404.7 1430.34   413.5 1428.98
   418.6 1428.31  426.111428.951   433.5 1430.84   439.5 1431.47   459.4 1430.87
   497.9  1432.4   502.5 1433.22     507 1435.92   534.1 1461.08   538.6  1464.3
   543.1 1466.36   574.8 1477.13   601.9 1487.34   642.4 1496.09     670 1503.61
#Mann= 7, -1 ,  0
       0     0.1       0     290    0.06       0  404.58     0.1       0
   413.5   0.045       0  426.11     0.1       0  454.58    0.07       0
  499.57     0.1       0
Bank Sta=413.5,426.11
XS Rating Curve= 0 ,0
Exp/Cntr(USF)=0,0
Exp/Cntr=0.3,0.1

Type RM Length L Ch R = 1 ,5334    ,58.7,77.7,95.8
XS GIS Cut Line= 2
 2199998.2205572 727875.889789352200377.15246921728239.613731641
#Sta/Elev= 30
       0 1494.93    24.9 1488.12    47.1 1481.05    92.8 1461.97     107 1458.05
   141.3 1438.75   152.2 1434.31   163.6 1433.66   177.7  1435.1     189 1434.15
   214.5 1434.55   246.7 1436.48   290.9 1436.37   319.1 1430.83   353.1 1430.56
  363.561426.793   367.2 1426.37   370.1 1426.78   379.7 1428.62   383.1 1430.18
   389.9 1436.48   406.8 1454.02     412 1458.25   418.5 1462.23   435.1 1468.66
   458.2 1479.03   474.7  1483.8   517.2 1493.11     520 1494.23   525.2 1498.71
#Mann= 5, -1 ,  0
       0     0.1       0     330    0.06       0  363.56   0.045       0
   370.1    0.06       0     470     0.1       0
Bank Sta=363.56,370.1
XS Rating Curve= 0 ,0
Exp/Cntr(USF)=0,0
Exp/Cntr=0.3,0.1

Type RM Length L Ch R = 1 ,5257    ,43.1,43.1,43.1
XS GIS Cut Line= 4
2199995.68589558727883.4937742062200225.07277208728135.692605272
2200112.28033005728232.0097467852200250.41938827728366.346812579
#Sta/Elev= 30
       0 1495.21    42.3 1483.16    66.7 1473.81    99.6 1460.03   121.2 1446.64
   140.3 1437.14   148.8 1434.34   157.3 1433.57   213.2 1433.78   259.2 1436.18
   290.4 1434.61   310.5 1430.46     354 1430.13   361.7 1429.57  368.571427.849
   376.7 1426.34   382.3 1427.87   394.7 1432.02     405 1432.48   410.7 1433.81
   429.4 1435.93   470.3 1437.61   489.2 1439.33   504.1 1443.81   531.1 1445.96
   578.4 1452.54   595.1 1455.78   611.4 1460.24   657.3 1474.95   681.9 1479.05
#Mann= 7, -1 ,  0
       0     0.1       0     310    0.06       0  368.57   0.045       0
   382.3    0.06       0  460.91    0.08       0  529.24    0.06       0
  599.24     0.1       0
Bank Sta=368.57,382.3
XS Rating Curve= 0 ,0
Exp/Cntr(USF)=0,0
Exp/Cntr=0.3,0.1

Type RM Length L Ch R = 1 ,5213    ,351.8,351.8,351.8
XS GIS Cut Line= 4
2199960.83429833727861.3154850422200190.22117482728113.514316108
2200077.42873279728209.8314576212200215.56779101728344.168523415
#Sta/Elev= 30
       0 1507.58    52.5 1493.58    88.2 1483.22   135.8 1463.49   145.8 1458.05
   156.6 1450.77     175 1440.12   183.3 1436.34   189.1 1434.62   200.5 1433.68
   248.7 1433.59   296.3 1435.29   314.1 1435.06   330.7 1433.64   340.9  1431.8
   359.2 1430.65  379.081425.839   384.7 1425.84   390.9 1427.11   435.8  1427.6
     467 1427.02   489.2  1424.8   499.2 1428.49   516.2 1429.42   527.5 1439.01
   538.8 1443.58   561.4 1444.91   626.5 1453.11   654.7  1460.4   681.9 1468.97
#Mann= 8, -1 ,  0
       0     0.1       0     340    0.06       0  379.08   0.045       0
   384.7    0.06       0  420.91     0.1       0  489.24    0.08       0
  579.24    0.06       0  629.24     0.1       0
Bank Sta=379.08,384.7
XS Rating Curve= 0 ,0
Exp/Cntr(USF)=0,0
Exp/Cntr=0.3,0.1

Type RM Length L Ch R = 1 ,4862    ,358,361.6,363.7
XS GIS Cut Line= 2
 2199714.3384559728193.989822504 2200160.4389008728515.891848085
#Sta/Elev= 30
       0 1521.35    17.1 1518.51    46.7 1510.13    61.5 1504.23    92.4 1489.56
   125.6  1476.9   135.4 1474.05   145.3 1469.66     165 1462.96   174.9 1458.13
   184.8 1452.32   195.6 1445.39   209.4 1434.75   218.5 1428.93  233.291421.844
   237.9 1421.09   241.4 1421.85   248.9 1425.15   253.8 1426.05   278.5 1427.19
   307.3 1427.48   321.6 1429.59   360.9 1430.21   393.3 1433.03   396.1 1433.79
   411.7 1440.89     419 1443.36   447.7 1450.84   507.8  1464.1   550.1 1470.49
#Mann= 6, -1 ,  0
       0     0.1       0     200    0.06       0  233.29   0.045       0
   241.4    0.06       0     400    0.05       0     520     0.1       0
Bank Sta=233.29,241.4
XS Rating Curve= 0 ,0
Exp/Cntr(USF)=0,0
Exp/Cntr=0.3,0.1

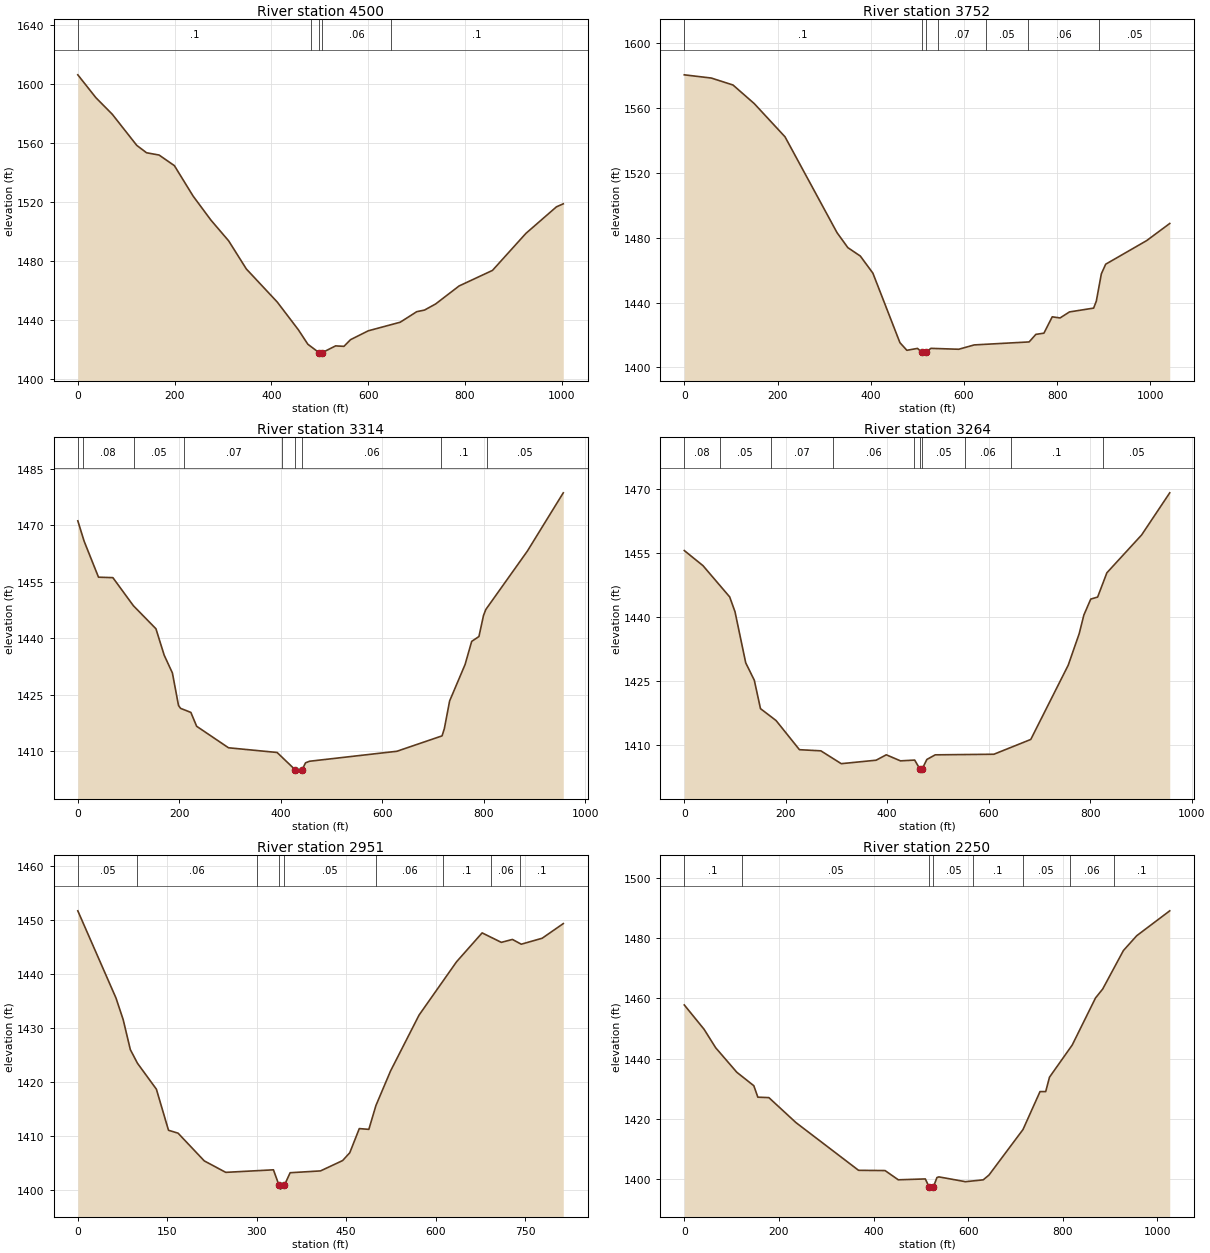
Type RM Length L Ch R = 1 ,4500    ,744,748.3,750.8
XS GIS Cut Line= 6
2199369.48404583728170.3872243322199425.00132325728251.705959335
2199479.72923218728331.6706944262199533.18975517728408.685632259
2199887.34521484728912.3135620062199944.23224017728992.695291013
#Sta/Elev= 30
       0 1606.31    37.3 1590.83    71.2 1579.59   121.9 1558.46   142.1 1553.47
     168 1551.92   199.6 1544.73   238.2 1524.15   275.1 1507.81   311.7 1493.77
   348.4 1474.65   412.2 1452.26     456 1433.37   475.4 1423.66   498.3 1418.02
   501.2 1417.63  505.291417.998   532.8 1422.54     550 1422.23   563.6 1426.74
   600.2 1432.75   666.3 1438.59   700.5 1445.73   716.5 1446.82   739.5 1450.96
     788 1463.17     857 1473.72   926.1 1498.82   989.2 1516.82  1003.3 1518.86
#Mann= 5, -1 ,  0
       0     0.1       0  481.57    0.06       0   498.3   0.045       0
  505.29    0.06       0  646.59     0.1       0
Bank Sta=498.3,505.29
XS Rating Curve= 0 ,0
Exp/Cntr(USF)=0,0
Exp/Cntr=0.3,0.1

Type RM Length L Ch R = 1 ,3752    ,450.6,437.7,424
XS GIS Cut Line= 6
2198885.88658784728640.3928460032199069.23103742728876.187978089
2199114.58429317728953.7055395842199160.49988376729122.672721341
2199253.38716517 729273.740004512199422.39863817729521.998038173
#Sta/Elev= 30
       0  1580.6      58 1578.61   104.5 1574.32   150.1 1562.84   216.1 1542.32
   327.7 1483.14   350.9  1473.9   377.7 1468.69   404.6 1458.14   462.6 1415.24
   477.5 1410.51   500.3 1411.69  509.58 1409.33   512.4 1408.77  518.291409.304
     529 1411.72   588.7 1411.16   622.1 1413.84   739.8 1415.69   754.2 1420.35
   771.5 1421.09   789.3 1431.19   806.1 1430.49   826.3  1434.2   878.1 1436.57
   883.9 1440.88   894.7 1457.75     904 1463.67   991.8 1478.23  1041.4 1488.82
#Mann= 7, -1 ,  0
       0     0.1       0  509.58   0.045       0  518.29     0.1       0
  543.63    0.07       0  646.38    0.05       0  736.38    0.06       0
  890.03    0.05       0
Bank Sta=509.58,518.29
XS Rating Curve= 0 ,0
Exp/Cntr(USF)=0,0
Exp/Cntr=0.3,0.1

Type RM Length L Ch R = 1 ,3314    ,47.8,50.3,51.5
XS GIS Cut Line= 5
2198742.68687659729084.8607972582198708.26554597729314.857870071
2198772.41438941729363.3606541332199135.40296691729374.312895696
2199382.61070503729507.304400383
#Sta/Elev= 30
       0 1471.23    12.5  1465.8    40.8 1456.24    69.1 1456.12   109.5 1448.66
     154 1442.52   170.2 1435.51   186.4 1430.78   198.5 1422.11   202.5 1421.36
   222.8 1420.28   234.2 1416.59     297 1410.87   392.8 1409.62   428.8 1404.97
   438.8 1404.66  441.921404.955   448.8 1406.87   456.8 1407.29   628.9 1409.94
   717.9 1414.04   722.4 1415.96   732.8 1423.32   763.3 1433.03   776.3 1439.17
   790.6 1440.46   799.6 1446.08   804.2 1447.66   885.9 1463.16   956.8 1478.68
#Mann= 9, -1 ,  0
       0     0.1       0      10    0.08       0     110    0.05       0
     210    0.07       0  402.98    0.06       0   428.8   0.045       0
  441.92    0.06       0  716.13     0.1       0  806.13    0.05       0
Bank Sta=428.8,441.92
XS Rating Curve= 0 ,0
Exp/Cntr(USF)=0,0
Exp/Cntr=0.3,0.1

Type RM Length L Ch R = 1 ,3264    ,315.3,313.2,308.5
XS GIS Cut Line= 5
2198693.40178956729128.6697635082198658.98045894729358.666836321
2198723.12930238729407.1696203832199086.11787988729418.121861946
  2199333.325618729551.113366633
#Sta/Elev= 30
       0 1455.57    36.9 1452.02    89.5 1444.69     100  1441.2   121.1 1429.23
     138 1425.15   150.2 1418.48   180.9 1415.69     227 1408.85   269.2 1408.58
   309.4 1405.57   378.1 1406.38   398.1 1407.65   426.1 1406.23   454.1 1406.41
  464.331404.318   466.1 1403.82   468.8 1404.31   478.1 1406.56   494.6 1407.64
   610.2 1407.78   682.9 1411.25   756.7 1428.67   778.4 1436.09   787.5 1440.42
   801.1 1444.18   814.7 1444.66   832.9 1450.35   901.4 1459.23   956.8 1469.11
#Mann= 10, -1 ,  0
       0    0.08       0      70    0.05       0     170    0.07       0
  292.56    0.06       0  452.98    0.05       0  464.33   0.045       0
   468.8    0.05       0  552.98    0.06       0  642.98     0.1       0
  826.13    0.05       0
Bank Sta=464.33,468.8
XS Rating Curve= 0 ,0
Exp/Cntr(USF)=0,0
Exp/Cntr=0.3,0.1

Type RM Length L Ch R = 1 ,2951    ,695.7,700.6,698.1
XS GIS Cut Line= 3
2198364.05223972729568.3240319462198866.29074566729573.017849758
2199116.62769566729759.205956321
#Sta/Elev= 30
       0  1451.7    64.1 1435.56    76.1 1431.58    88.1 1426.04     100 1423.53
   131.8 1418.72   152.1 1411.13   168.1  1410.6   212.1 1405.47   248.1 1403.35
   328.1 1403.82  337.541400.935   340.1 1400.25  346.471400.969   356.1 1403.28
   407.1 1403.62   444.1 1405.53   456.1 1406.97   472.1 1411.44   488.1  1411.3
     500 1415.71   524.5 1422.09   572.3 1432.42   635.2 1442.28   678.1 1447.62
   710.3 1445.87   728.9 1446.41   743.8 1445.53   778.8 1446.63   814.2 1449.34
#Mann= 9, -1 ,  0
       0    0.05       0     100    0.06       0     300    0.05       0
  337.54   0.045       0  346.47    0.05       0     500    0.06       0
  612.26     0.1       0  692.26    0.06       0  742.26     0.1       0
Bank Sta=337.54,346.47
XS Rating Curve= 0 ,0
Exp/Cntr(USF)=0,0
Exp/Cntr=0.3,0.1

Type RM Length L Ch R = 1 ,2250    ,743.8,744.6,733.8
XS GIS Cut Line= 6
 2198154.6465805  730155.88784652198450.60399383730115.910892338
2198621.32838993730117.5411384252198794.17778176730152.101764843
2198977.23843926730149.2280829252199173.69145842 730133.87312676
#Sta/Elev= 30
       0 1457.81    41.9 1449.71    66.4 1443.57     111 1435.44     147 1430.96
   155.5 1427.15   178.8 1427.01   236.1  1418.7   368.4 1402.84   424.4 1402.76
   452.4 1399.69   509.5 1399.98   517.7 1397.26   521.8 1396.59   526.51397.284
   534.1 1400.44   538.2 1400.66   594.4 1399.06   631.8 1399.67     644 1401.25
     716  1416.4     752 1429.01     764 1429.01     772 1433.79   820.1  1444.5
   869.3 1460.13   884.5 1463.11   928.3  1475.9   956.4 1480.82  1026.2 1489.09
#Mann= 8, -1 ,  0
       0     0.1       0  121.17    0.05       0   517.7   0.045       0
   526.5    0.05       0  610.92     0.1       0  715.99    0.05       0
  814.33    0.06       0  909.14     0.1       0
Bank Sta=517.7,526.5
XS Rating Curve= 0 ,0
Exp/Cntr(USF)=0,0
Exp/Cntr=0.3,0.1

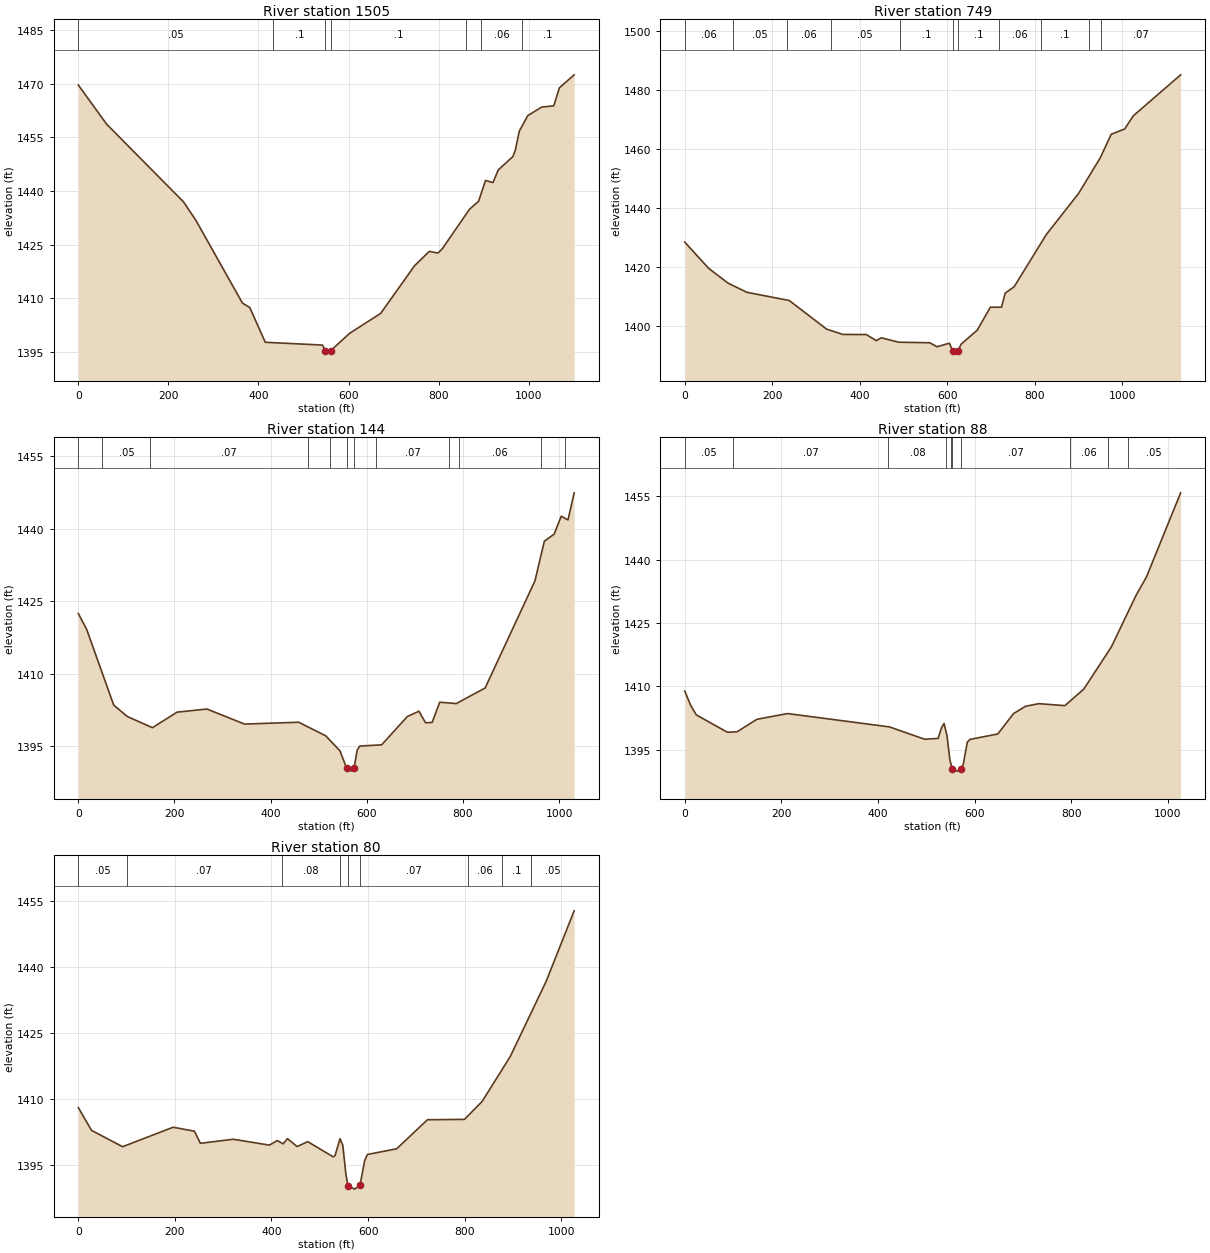
Type RM Length L Ch R = 1 ,1505    ,752.8,756.1,743.5
XS GIS Cut Line= 6
2198238.69824967730820.067948595 2198554.7130376730758.585460007
2198653.25286676730737.2584029292198833.57009143730723.165255249
2198994.66130467730625.8032452612199254.12141567730457.750103667
#Sta/Elev= 30
       0 1469.61    62.6 1458.71   233.7 1436.95   260.9 1431.84   364.4 1408.69
   380.7 1407.44   415.2 1397.73   542.1 1396.95  548.61 1395.39   554.1  1394.7
  560.471395.415   602.2 1400.21   671.5 1405.82   746.5  1419.1   779.5 1423.14
   798.4 1422.65   807.9 1423.81   868.7 1434.91   888.7 1437.11   904.2 1442.95
   920.8 1442.35   932.4 1445.88   964.9 1449.62     970 1451.26   979.3 1456.76
   998.1 1461.08    1029 1463.45  1055.7 1463.79  1068.2 1468.82    1101 1472.46
#Mann= 7, -1 ,  0
       0    0.05       0  432.76     0.1       0  548.61   0.045       0
  560.47     0.1       0  861.89    0.07       0  894.87    0.06       0
  984.87     0.1       0
Bank Sta=548.61,560.47
XS Rating Curve= 0 ,0
Exp/Cntr(USF)=0,0
Exp/Cntr=0.3,0.1

Type RM Length L Ch R = 1 ,749     ,612.4,605.5,593.6
XS GIS Cut Line= 6
2198475.63543984731354.0501483382198656.50089176731223.441485673
2198747.58469909731151.9836233412198911.99447526 731011.36185734
2199090.50855392730953.3458972572199445.55836876730792.736638427
#Sta/Elev= 30
       0 1428.51    54.6 1419.64    98.8 1414.66   141.5 1411.57   238.7 1408.78
     324 1399.11   361.1 1397.31   414.7 1397.28   437.6 1395.22   448.9 1396.18
   488.7 1394.69   559.7 1394.51   576.4 1393.16   604.5 1394.35  612.021391.744
     615    1391   624.6 1391.77     631 1393.99   668.3 1398.79   698.1 1406.52
   723.6 1406.53     732 1411.27   752.6 1413.46   825.9 1431.07   899.8 1444.99
   949.1 1456.98   974.2 1464.96  1004.9 1466.76  1024.9 1471.23  1132.8 1485.06
#Mann= 11, -1 ,  0
       0    0.06       0  109.93    0.05       0   233.1    0.06       0
   333.1    0.05       0  491.42     0.1       0  612.02   0.045       0
   624.6     0.1       0  717.96    0.06       0  813.07     0.1       0
  922.94    0.06       0  950.68    0.07       0
Bank Sta=612.02,624.6
XS Rating Curve= 0 ,0
Exp/Cntr(USF)=0,0
Exp/Cntr=0.3,0.1

Type RM Length L Ch R = 1 ,144     ,56.6,55.8,57.3
XS GIS Cut Line= 6
2198518.94822753731478.7078816352198784.93123691 731506.87078851
2198977.37776722 731369.185466012199047.78503441731290.955169135
2199088.46478878 731231.500143512199291.86356066730946.741862885
#Sta/Elev= 30
       0 1422.47    17.3  1419.2    73.6 1403.54   101.8 1401.18   154.1 1398.86
   205.5 1402.08   267.5 1402.72   345.6 1399.61   458.4 1399.99   514.6 1397.18
   544.2 1394.08   557.9 1390.53   568.1 1389.88  573.561390.527     580 1394.22
   585.4 1395.06   630.9 1395.32   684.2 1401.16   708.4 1402.27   722.2 1399.88
   735.9 1399.95   751.7 1404.13   786.1 1403.85   846.1 1407.07   949.7 1429.21
   969.3 1437.43   989.7 1438.89  1004.3 1442.58  1018.5 1441.83  1031.3 1447.43
#Mann= 12, -1 ,  0
       0     0.1       0      50    0.05       0     150    0.07       0
  477.47    0.08       0   524.1    0.05       0   557.9   0.045       0
  573.56    0.05       0  619.35    0.07       0  771.39     0.1       0
  791.39    0.06       0  961.39    0.05       0 1011.39    0.06       0
Bank Sta=557.9,573.56
XS Rating Curve= 0 ,0
Exp/Cntr(USF)=0,0
Exp/Cntr=0.3,0.1

Type RM Length L Ch R = 1 ,88      ,8.3,8.3,8.3
XS GIS Cut Line= 6
2198568.36286904731502.1769706982198818.69981904731528.775271636
2199048.69689185 731369.185466012199097.19967591731314.424258198
2199137.87943029731254.9692325732199341.27820216730970.210951947
#Sta/Elev= 30
       0 1408.87    11.9 1405.54    23.9 1403.22    88.3 1399.11   108.4 1399.23
   149.4 1402.19     213 1403.54   423.9 1400.38     497 1397.45   524.7 1397.66
   531.7 1400.22   536.9 1401.19     543 1398.31     549 1392.55     554  1390.4
   565.3  1389.9   572.41390.387   576.7 1391.58   585.1 1396.76   590.5 1397.42
   648.2 1398.71   680.8 1403.54   705.6 1405.27   733.2 1405.89   787.2 1405.42
   826.5 1409.38   883.4 1419.35   934.7 1431.61   956.1 1435.93  1026.8 1455.86
#Mann= 10, -1 ,  0
       0    0.05       0     100    0.07       0  421.75    0.08       0
  541.69     0.1       0  551.69    0.07       0     554   0.045       0
   572.4    0.07       0  796.88    0.06       0  876.88     0.1       0
  916.88    0.05       0
Bank Sta=554,572.4
XS Rating Curve= 0 ,0
Exp/Cntr(USF)=0,0
Exp/Cntr=0.3,0.1

Type RM Length L Ch R = 1 ,80      ,,,
XS GIS Cut Line= 6
2198569.01561753731513.9115152292198819.35256753731540.509816167
2199049.34964035731380.9200105422199097.85242441731326.158802729
2199138.53217878731266.7037771042199341.93095066730981.945496479
#Sta/Elev= 30
       0 1408.09    27.3 1402.93    91.7 1399.23   196.3 1403.64   240.5 1402.74
   252.7    1400   320.9 1400.92   395.6 1399.59     412 1400.62   424.3 1399.89
     433 1401.07   453.1 1399.27   475.1 1400.38   527.8 1396.93   531.7 1397.24
     542 1401.06   547.7 1399.54     554  1393.1   558.1 1390.43   572.1 1389.62
  583.311390.469     593 1396.11   598.7 1397.47   659.3 1398.76     723 1405.34
   799.6 1405.42   836.1 1409.47   894.2 1419.61   968.9 1436.71  1026.8 1452.67
#Mann= 9, -1 ,  0
       0    0.05       0     100    0.07       0  421.75    0.08       0
  541.69     0.1       0   558.1   0.045       0  583.31    0.07       0
  806.88    0.06       0  876.88     0.1       0  936.88    0.05       0
Bank Sta=558.1,583.31
XS Rating Curve= 0 ,0
Exp/Cntr(USF)=0,0
Exp/Cntr=0.3,0.1
LCMann Table=0

Chan Stop Cuts=-1
Use User Specified Reach Order=0
Composite Channel Slope=5